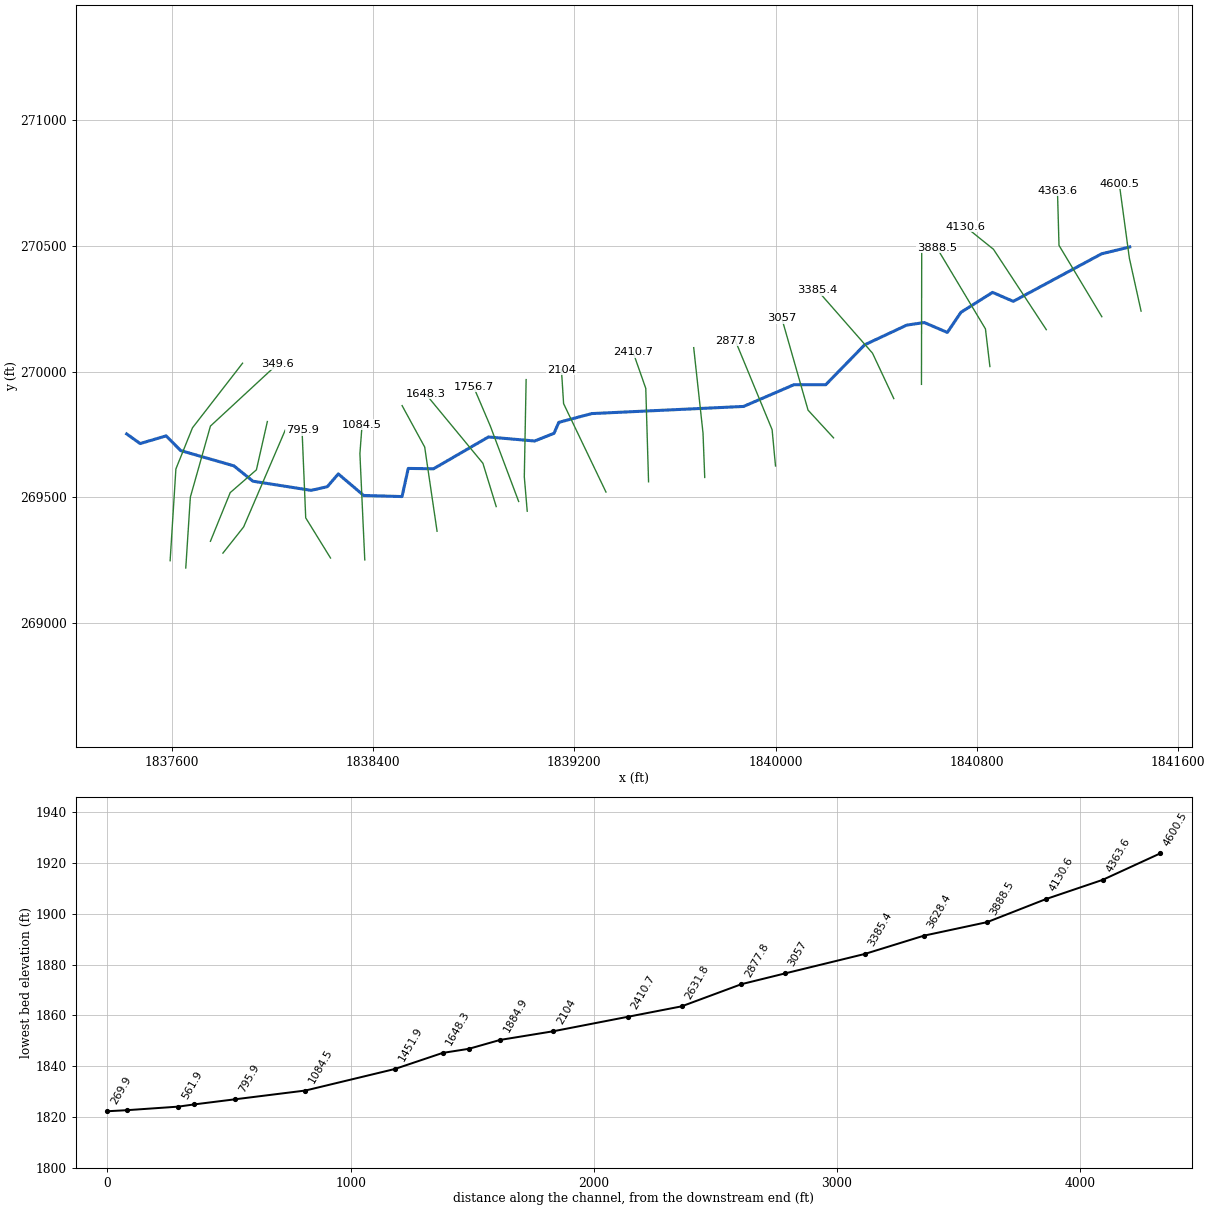
--- TroughFk.prj (project) ---

Proj Title=TroughFk
Current Plan=p01
Default Exp/Contr=0,0
English Units
Geom File=g01
Flow File=f01
Plan File=p01
BEGIN DESCRIPTION:
END DESCRIPTION:
DSS Export Rating Curves= 0
DSS Export Rating Curve Sorted= 0
DSS Export Volume Flow Curves= 0
DXF OffsetX= 0
DXF OffsetY= 0
DXF ScaleX= 0
DXF ScaleY= 0

--- TroughFk.p01 (plan) ---

Plan Title=Floodplain
Program Version=4.00
Geom File=g01
Flow File=f01
K Sum by GR=0
Std Step Tol=0.01
Critical Tol=0.01
Num of Std Step Trials=20
Max Error Tol=0.3
Flow Tol Ratio=0.001
Split Flow NTrial=30
Split Flow Tol=0.02
Split Flow Ratio=0.02
Log Output Level=0
Friction Slope Method=1
Unsteady Friction Slope Method=2
Unsteady Bridges Friction Slope Method=1
Global Log Level=0
CheckData=False
Run HTab=0
Run UNet=0
Run PostProcess=0
UNET Theta=0
UNET Theta Warmup=0
UNET ZTol=0
UNET ZSATol=0
UNET MxIter=0
UNET MaxInSteps=0
UNET DtIC=0
UNET DtMin=0
UNET MaxCRTS=0
UNET WFStab=0
UNET SFStab=0
UNET WFX=0
UNET SFX=0
UNET DSS MLevel=0
UNET DZMax Abort=0
UNET Convert EG Bridges=0
UNET Use Existing IB Tables=0
UNET Froude Limit=0
UNET Froude Power=0
Write IC File=0
Echo Input=False
Echo Output=False
Write Detailed=0

--- TroughFk.f01 (steady flow) ---

Flow Title=NFF Regression Equation
Program Version=4.00
Number of Profiles=1
Profile Names=P100yr
River Rch & RM=TroughFk,Main      ,4600.5
305.8458
River Rch & RM=TroughFk,Main      ,4600.5
305.8458
River Rch & RM=TroughFk,Main      ,4600.5
488.2585
River Rch & RM=TroughFk,Main      ,4363.6
553.4621
River Rch & RM=TroughFk,Main      ,4363.6
352.3306
River Rch & RM=TroughFk,Main      ,4363.6
352.3306
River Rch & RM=TroughFk,Main      ,3385.4
365.6120
River Rch & RM=TroughFk,Main      ,3385.4
570.2484
River Rch & RM=TroughFk,Main      ,3385.4
365.6120
River Rch & RM=TroughFk,Main      ,3057
404.5425
River Rch & RM=TroughFk,Main      ,3057
404.5425
River Rch & RM=TroughFk,Main      ,3057
622.5393
River Rch & RM=TroughFk,Main      ,1884.9
679.9256
River Rch & RM=TroughFk,Main      ,1884.9
447.2147
River Rch & RM=TroughFk,Main      ,1884.9
447.2147
River Rch & RM=TroughFk,Main      ,561.9
495.7525
River Rch & RM=TroughFk,Main      ,561.9
741.6718
River Rch & RM=TroughFk,Main      ,561.9
495.7525
River Rch & RM=TroughFk,Main      ,269.9
495.7525
River Rch & RM=TroughFk,Main      ,269.9
495.7525
River Rch & RM=TroughFk,Main      ,269.9
742.9351
Boundary for River Rch & Prof#=TroughFk,Main      ,1
Up Type=0
Dn Type=3
Dn Slope=0.009944

--- TroughFk.g01 (geometry) ---

Geom Title=USGS 10m DEM
Program Version=4.00

River Reach=TroughFk        ,Main
Reach XY= 30
     1841407.949      270496.216     1841295.849      270468.752
     1840945.025       270279.51     1840862.653      270315.277
     1840736.859      270235.839     1840682.998      270155.775
     1840591.289      270195.079     1840521.415      270184.889
     1840354.009      270106.282     1840199.704       269947.61
     1840072.814      269947.497     1839872.925      269861.049
      1839269.51      269832.609     1839138.496      269797.672
     1839119.572      269754.001      1839042.42      269723.431
     1838859.001      269739.444     1838640.645      269612.798
     1838540.202      269614.253     1838515.455      269502.164
     1838362.953      269506.591     1838262.162      269592.418
     1838218.491      269541.469      1838154.44      269526.912
     1837922.984      269563.304     1837847.287      269624.443
      1837636.03      269685.213     1837577.982      269743.811
     1837474.626      269713.242     1837420.945      269751.687

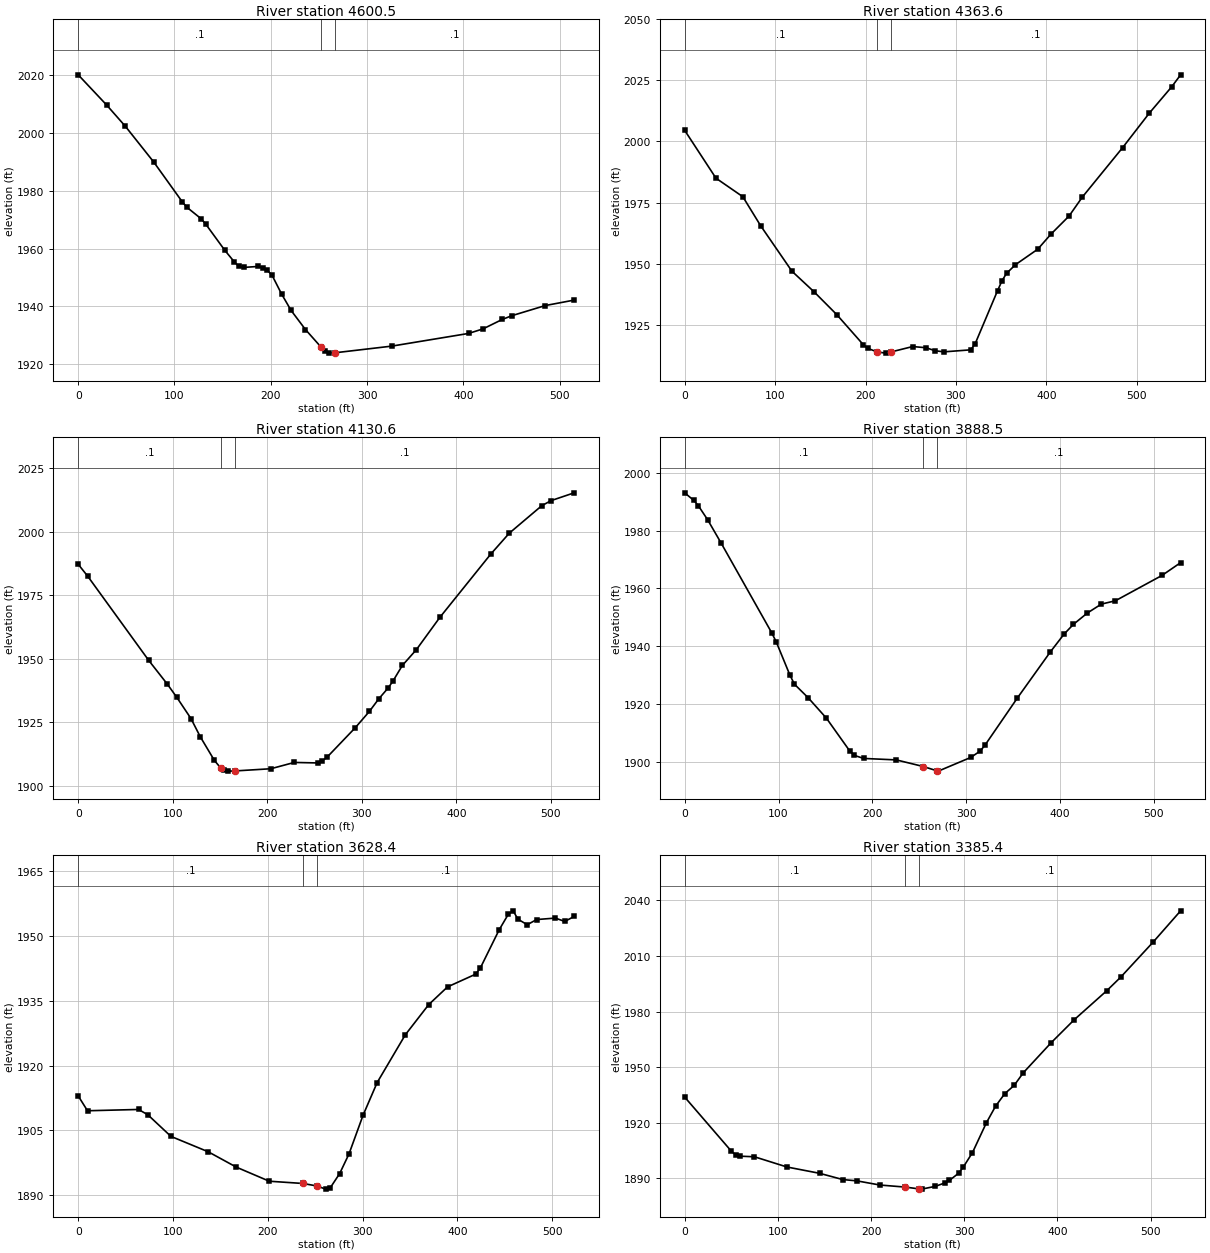
Type RM Length L Ch R = 1 ,4600.5  ,227.8,236.9,246
XS GIS Cut Line= 3
      1841452.96      270240.606     1841406.374      270451.679
     1841366.282      270747.971
#Sta/Elev= 30
       0 2020.22    29.5 2009.77    49.1 2002.34    78.6 1989.95   108.1 1976.23
     113 1974.31   127.7 1970.37   132.6 1968.45   152.3 1959.43   162.1 1955.45
     167 1953.83   171.9 1953.51   186.7 1953.84   191.6 1953.36   196.5 1952.51
   201.4 1950.77   211.2 1944.34   221.1 1938.63   236.1 1931.98     252 1926.01
     256 1924.62     261 1923.82     267 1923.95   325.8 1926.25   405.5 1930.64
   420.5 1932.21   440.4 1935.47   450.4 1936.78   485.2  1940.3   515.2 1942.19
#Mann= 3 , 0 , 0
       0      .1       0     252    .045       0     267      .1       0
Bank Sta=252,267
XS Rating Curve= 0 ,0
Exp/Cntr=0.3,0.1

Type RM Length L Ch R = 1 ,4363.6  ,233.2,233,232.3
XS GIS Cut Line= 3
     1841296.932      270218.432     1841126.706      270502.528
     1841120.618      270719.655
#Sta/Elev= 30
       0 2004.54    34.6 1984.96    64.3 1977.38      84 1965.51   118.6 1946.91
   143.4 1938.36   168.1 1929.18   197.7 1916.77   202.7 1915.32   212.9 1913.88
   222.4  1913.4   227.9 1913.86   252.1 1916.09   266.9 1915.61   276.8 1914.38
   286.7 1913.92   316.4 1914.75   321.3 1917.32     346 1938.98   350.9 1943.01
   355.9 1946.03   365.8 1949.58   390.4 1955.91   405.2 1962.14     425 1969.46
   439.8 1977.27   484.2 1997.43   513.8 2011.58   538.5 2022.33   548.4 2027.24
#Mann= 3 , 0 , 0
       0      .1       0   212.9    .045       0   227.9      .1       0
Bank Sta=212.9,227.9
XS Rating Curve= 0 ,0
Exp/Cntr=0.3,0.1

Type RM Length L Ch R = 1 ,4130.6  ,243,242.1,241.2
XS GIS Cut Line= 3
     1841076.193      270166.843     1840866.313      270486.794
     1840755.767      270575.959
#Sta/Elev= 30
       0 1987.26     9.9 1982.65    74.5 1949.48    94.4 1940.03   104.4 1934.84
   119.3 1926.53   129.2 1919.33   144.1 1910.04   150.7 1907.11     154 1906.19
     159 1905.84   165.7 1905.91   203.8 1906.78   228.6 1909.26   253.4 1909.06
   258.4 1909.94   263.4 1911.37   293.2 1922.96   308.1 1929.37     318  1934.3
     328 1938.62     333  1941.3   342.9 1947.43   357.8 1953.67   382.6 1966.36
   436.5 1991.29   456.1 1999.52   490.4 2010.32   500.2 2012.32   524.7  2015.4
#Mann= 3 , 0 , 0
       0      .1       0   150.7    .045       0   165.7      .1       0
Bank Sta=150.7,165.7
XS Rating Curve= 0 ,0
Exp/Cntr=0.3,0.1

Type RM Length L Ch R = 1 ,3888.5  ,273.6,260.2,246.4
XS GIS Cut Line= 3
     1840852.077      270020.046     1840834.326      270170.055
     1840640.432      270493.979
#Sta/Elev= 30
       0 1993.04     9.8 1990.41    14.6 1988.56    24.4 1983.76      39 1975.57
    92.6 1944.71    97.5 1941.54   112.1 1930.02     117 1926.82   131.6 1922.14
   151.1 1915.06   175.9 1903.74   180.9 1902.19   190.8 1901.14   225.6 1900.63
   254.4 1898.34   269.4 1896.81   270.3 1896.75     305  1901.5     315 1903.71
     320 1905.69   354.7  1922.1   389.5 1937.89   404.4 1944.17   414.3 1947.52
   429.2 1951.46   444.1 1954.54     459 1955.68   508.7 1964.45   528.6 1968.88
#Mann= 3 , 0 , 0
       0      .1       0   254.4    .045       0   269.4      .1       0
Bank Sta=254.4,269.4
XS Rating Curve= 0 ,0
Exp/Cntr=0.3,0.1

Type RM Length L Ch R = 1 ,3628.4  ,226.3,243,259.7
XS GIS Cut Line= 2
     1840580.079      269949.014     1840581.059      270472.214
#Sta/Elev= 30
       0 1912.99     9.8 1909.56    63.6 1909.86    73.4 1908.64    97.8 1903.63
   137.2 1900.06   166.9  1896.5   201.6 1893.25     237 1892.73     252 1892.15
     261 1891.42   265.9 1891.73   275.8 1895.01   285.7 1899.58   300.5 1908.52
   315.4  1916.1   345.1 1927.15   369.8 1934.14   389.6 1938.23   419.3 1941.18
   424.2 1942.59     444 1951.41   453.9 1955.11   458.9 1955.84   463.8 1953.92
   473.7 1952.62   483.6 1953.82   503.4 1954.16   513.3 1953.38   523.2 1954.54
#Mann= 3 , 0 , 0
       0      .1       0     237    .045       0     252      .1       0
Bank Sta=237,252
XS Rating Curve= 0 ,0
Exp/Cntr=0.3,0.1

Type RM Length L Ch R = 1 ,3385.4  ,337.9,328.4,318.9
XS GIS Cut Line= 3
     1840470.081      269892.385     1840385.487      270073.247
     1840166.446      270323.579
#Sta/Elev= 30
       0  1933.9    49.9 1904.82    54.9  1902.6    59.9 1901.99    74.9 1901.68
   109.8 1896.16   144.8 1892.76   169.7 1889.38   184.7 1888.69   209.6 1886.43
     237 1885.31     252 1884.31   254.3 1884.22   269.2 1885.74   279.1 1887.56
   284.1  1888.9     294  1892.8     299 1896.09   308.9 1903.94   323.8    1920
   333.7 1928.99   343.6 1935.77   353.6 1940.17   363.5 1947.05   393.3 1963.22
   418.1 1975.64   452.9 1991.25   467.8 1998.52   502.5 2017.38   532.3 2034.42
#Mann= 3 , 0 , 0
       0      .1       0     237    .045       0     252      .1       0
Bank Sta=237,252
XS Rating Curve= 0 ,0
Exp/Cntr=0.3,0.1

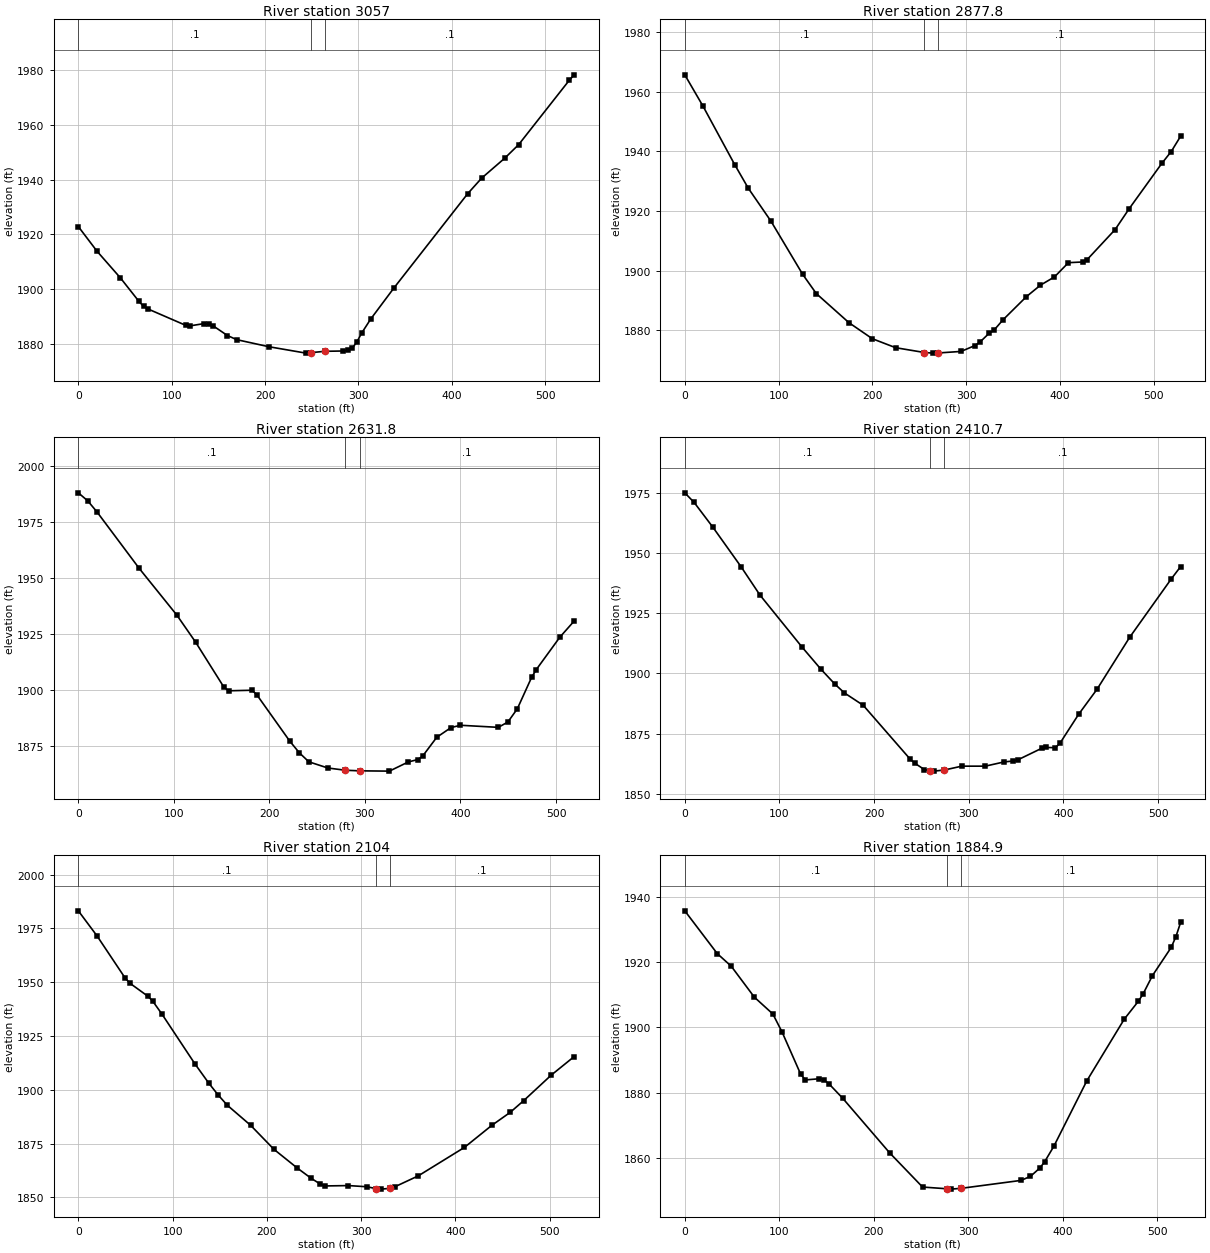
Type RM Length L Ch R = 1 ,3057    ,176.9,179.1,181.4
XS GIS Cut Line= 3
      1840230.58      269735.989     1840129.287      269846.383
     1840024.656      270213.081
#Sta/Elev= 30
       0 1922.81      20 1913.81      45 1904.08    64.9 1895.48    69.9 1893.61
    74.9 1892.65   114.9 1886.73   119.9 1886.53   134.8 1887.35   139.8  1887.1
   144.8 1886.44   159.7 1882.99   169.6 1881.48   204.3 1878.88   243.9 1876.55
   249.4 1876.74   264.4 1877.22   283.5 1877.33   288.5 1877.54   293.4 1878.35
   298.4 1880.61   303.4  1883.8   313.2 1888.99     338 1900.32   417.2 1934.86
   432.1 1940.52   456.9 1947.83   471.7 1952.75   526.2 1976.39   531.2 1978.28
#Mann= 3 , 0 , 0
       0      .1       0   249.4    .045       0   264.4      .1       0
Bank Sta=249.4,264.4
XS Rating Curve= 0 ,0
Exp/Cntr=0.3,0.1

Type RM Length L Ch R = 1 ,2877.8  ,252.8,246,239.3
XS GIS Cut Line= 3
     1839999.916      269623.839     1839986.478      269768.303
      1839840.37      270122.865
#Sta/Elev= 30
       0 1965.73    19.4 1955.22    53.2 1935.59    67.7 1927.66    91.9 1916.59
   125.7 1898.75   140.2 1892.31     175 1882.54   199.9 1877.16   224.8 1874.14
   255.4 1872.53   264.6 1872.32   270.4 1872.38   294.5 1872.89   309.4 1874.87
   314.4 1875.95   324.4 1878.97   329.4 1879.94   339.3 1883.52   364.2 1891.28
   379.2 1895.14   394.1  1897.9     409 1902.68     424 1902.91     429 1903.73
   458.8 1913.81   473.8 1920.82   508.6 1936.03   518.6 1939.99   528.6 1945.13
#Mann= 3 , 0 , 0
       0      .1       0   255.4    .045       0   270.4      .1       0
Bank Sta=255.4,270.4
XS Rating Curve= 0 ,0
Exp/Cntr=0.3,0.1

Type RM Length L Ch R = 1 ,2631.8  ,223.3,221.1,218.9
XS GIS Cut Line= 3
     1839718.634      269578.314     1839711.802      269754.993
     1839674.801      270095.178
#Sta/Elev= 30
       0 1988.19     9.8 1984.62    19.6  1979.6    63.8 1954.31   103.1 1933.45
   122.8 1921.31   152.2 1901.29   157.2 1899.56   181.8  1899.8   186.7 1897.85
   221.4 1876.97   231.4 1871.77   241.3 1867.76   261.1    1865   279.6 1863.98
   294.6 1863.72   325.6 1863.59   345.4  1867.7   355.4 1868.78   360.3 1870.26
   375.2 1878.75   390.1 1883.09     400 1884.12   439.6 1883.19   449.6 1885.57
   459.5 1891.49   474.4 1905.51   479.3 1909.02   504.1  1923.6     519 1930.79
#Mann= 3 , 0 , 0
       0      .1       0   279.6    .045       0   294.6      .1       0
Bank Sta=279.6,294.6
XS Rating Curve= 0 ,0
Exp/Cntr=0.3,0.1

Type RM Length L Ch R = 1 ,2410.7  ,297.1,306.7,316.3
XS GIS Cut Line= 3
     1839495.364      269561.022     1839484.318      269932.866
     1839434.214      270076.105
#Sta/Elev= 30
       0 1974.88     9.9 1970.88    29.8 1960.55    59.5  1944.2    79.4 1932.49
     124 1910.85   143.8 1901.74   158.7  1895.5   168.6 1891.92   188.5 1886.77
   238.1 1864.44     243 1862.75     253 1860.15   259.1 1859.51   262.9 1859.48
   274.1 1859.93   292.6 1861.54   317.4 1861.54   337.3 1863.29   347.2 1863.69
   352.2 1864.23   376.9 1868.92   381.8 1869.29   391.6  1869.2   396.5 1871.15
   416.1 1883.07   435.6 1893.49   469.9 1914.93     514 1939.23   523.8 1944.29
#Mann= 3 , 0 , 0
       0      .1       0   259.1    .045       0   274.1      .1       0
Bank Sta=259.1,274.1
XS Rating Curve= 0 ,0
Exp/Cntr=0.3,0.1

Type RM Length L Ch R = 1 ,2104    ,229.4,219.1,208.8
XS GIS Cut Line= 3
     1839326.022      269520.258     1839157.612      269872.365
     1839149.111      270007.869
#Sta/Elev= 30
       0 1983.21    19.8 1971.57    49.4 1952.13    54.4 1949.64    74.1 1943.39
      79 1941.17    88.9 1935.07   123.5 1912.17   138.3 1903.13   148.2 1897.64
   158.1 1892.78   182.8 1883.47   207.5 1872.31   232.2 1863.62     247 1858.83
   256.9 1856.08   261.8 1855.26   286.6 1855.43   306.3 1854.88   315.6 1854.04
   321.1 1853.78   330.6 1854.13     336  1854.9   360.7 1859.95   409.7 1873.19
   438.8 1883.46   458.2 1889.47   472.7 1894.99   501.8 1906.81   526.1 1915.42
#Mann= 3 , 0 , 0
       0      .1       0   315.6    .045       0   330.6      .1       0
Bank Sta=315.6,330.6
XS Rating Curve= 0 ,0
Exp/Cntr=0.3,0.1

Type RM Length L Ch R = 1 ,1884.9  ,119.3,128.2,137
XS GIS Cut Line= 3
     1839013.081      269443.849     1839001.519       269580.75
     1839008.779      269967.957
#Sta/Elev= 30
       0 1935.81    34.4 1922.66    49.1 1918.82    73.6  1909.3    93.2 1904.13
     103 1898.56   122.7  1885.6   127.6 1883.89   142.4 1884.25   147.3 1883.91
   152.3 1882.77   167.2 1878.23   216.8 1861.49   251.6    1851   277.3 1850.47
   281.4 1850.36   292.3  1850.6   355.8 1853.04   365.8 1854.28   375.7 1856.84
   380.7 1858.72   390.6 1863.55   425.4 1883.59   465.1 1902.57     480 1908.06
   484.9 1910.25   494.9 1915.93   514.7 1924.56   519.7 1927.87   524.7 1932.25
#Mann= 3 , 0 , 0
       0      .1       0   277.3    .045       0   292.3      .1       0
Bank Sta=277.3,292.3
XS Rating Curve= 0 ,0
Exp/Cntr=0.3,0.1

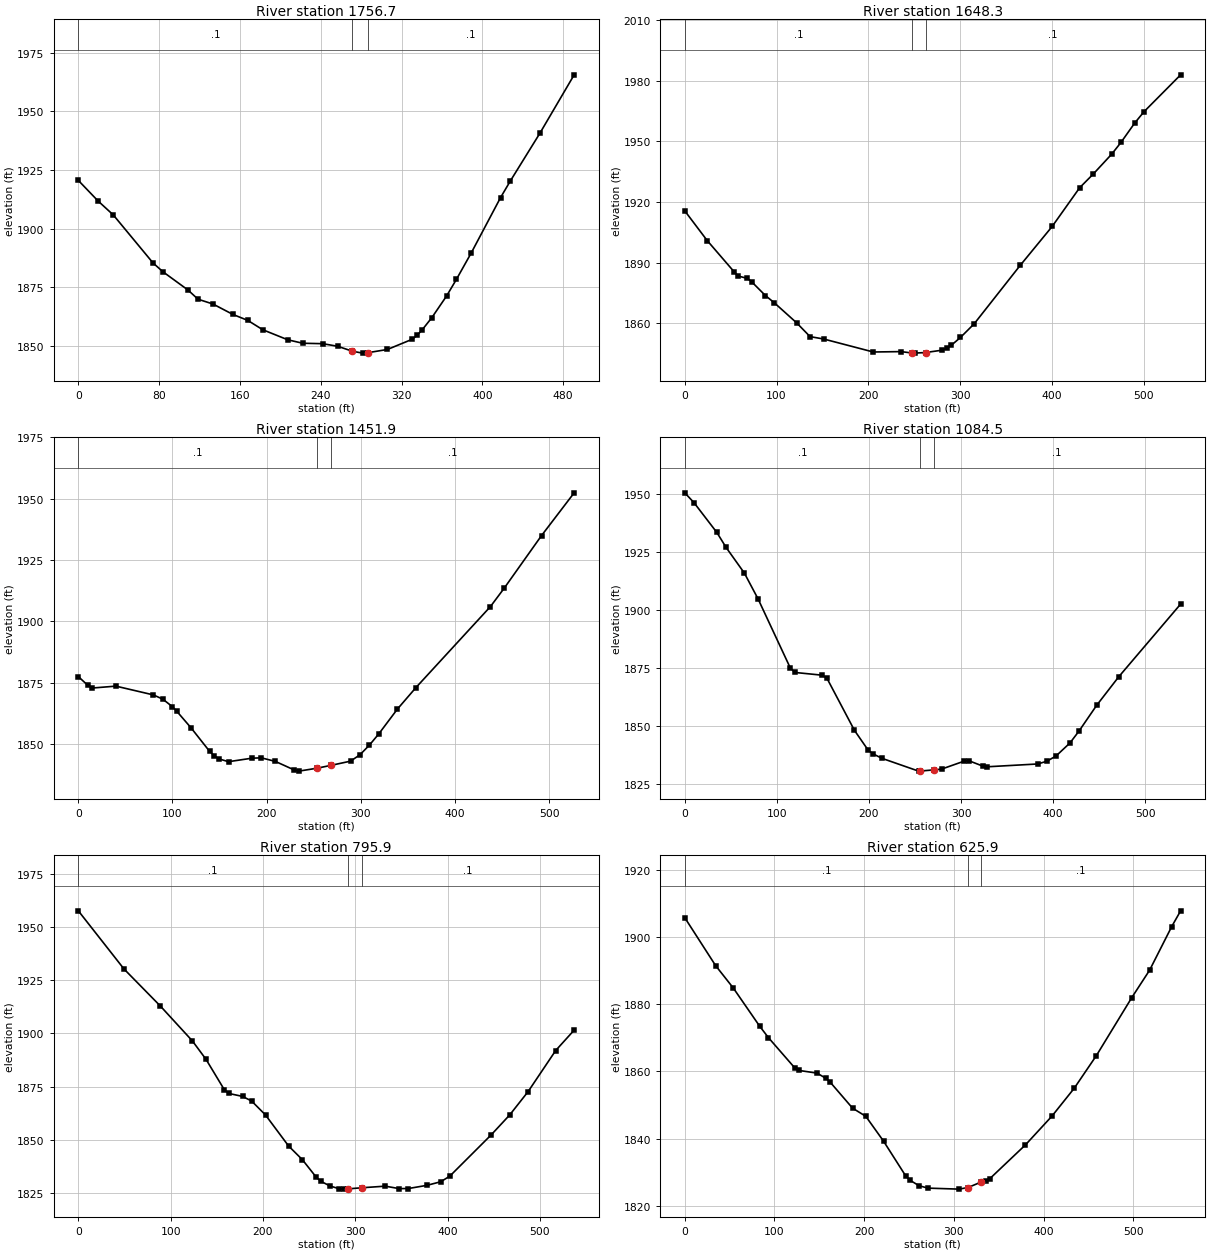
Type RM Length L Ch R = 1 ,1756.7  ,100.8,108.3,115.9
XS GIS Cut Line= 3
     1838979.065       269482.65     1838866.368      269783.061
     1838799.803      269939.514
#Sta/Elev= 30
       0 1920.58    19.7 1911.73    34.6 1905.85      74 1885.33    83.9 1881.55
   108.6 1873.79   118.5 1869.88   133.3 1867.83     153 1863.39   167.8 1860.83
   182.6 1856.85   207.3 1852.57   222.1 1851.09   241.9  1850.9   256.7  1849.8
   271.4 1847.68   281.4 1846.87   286.4 1847.04     306 1848.43   330.6 1852.79
   335.4 1854.49   340.3 1856.74     350 1862.02   364.6 1871.26   374.3 1878.33
   388.9 1889.55     418 1913.23   427.7 1920.33   456.9 1940.66   490.9 1965.64
#Mann= 3 , 0 , 0
       0      .1       0   271.4    .045       0   286.4      .1       0
Bank Sta=271.4,286.4
XS Rating Curve= 0 ,0
Exp/Cntr=0.3,0.1

Type RM Length L Ch R = 1 ,1648.3  ,208.4,196.5,183.9
XS GIS Cut Line= 3
     1838889.857      269462.228     1838837.001      269634.723
     1838608.146      269912.471
#Sta/Elev= 30
       0 1915.61    24.4 1900.93    53.6 1885.55    58.5 1883.33    68.3 1882.21
    73.1 1880.43    87.8 1873.74    97.5 1870.16   121.9 1860.21   136.5  1853.4
   151.2 1852.24   205.4  1845.8   235.4 1845.99   247.6 1845.31   250.4 1845.24
   262.6 1845.55   280.4  1846.7   285.4 1847.63   290.4 1849.12   300.4    1853
   315.4 1859.78   365.4  1888.6   400.3 1907.89   430.3 1927.07   445.3 1933.93
   465.3 1943.73   475.3 1949.48   490.3 1959.08   500.3 1964.62   540.3 1982.91
#Mann= 3 , 0 , 0
       0      .1       0   247.6    .045       0   262.6      .1       0
Bank Sta=247.6,262.6
XS Rating Curve= 0 ,0
Exp/Cntr=0.3,0.1

Type RM Length L Ch R = 1 ,1451.9  ,368.8,367.4,370
XS GIS Cut Line= 3
     1838654.768      269364.073     1838605.568      269699.375
      1838515.83      269864.251
#Sta/Elev= 30
       0 1877.48      10 1873.93      15 1872.81    39.9 1873.58    79.7    1870
    89.7 1868.27    99.7 1865.26   104.7 1863.26   119.6 1856.62   139.5 1846.94
   144.5 1845.13   149.5 1843.88   159.5 1842.76   184.4 1844.19   194.4 1844.33
   209.3 1842.87   229.2  1839.4   234.2 1838.91   253.2 1840.08   268.2 1841.25
   289.1 1842.98     299 1845.55     309 1849.46     319 1854.05   338.9 1864.23
   358.6 1873.01   437.7 1906.04   452.5 1913.64     492 1935.02   526.6 1952.43
#Mann= 3 , 0 , 0
       0      .1       0   253.2    .045       0   268.2      .1       0
Bank Sta=253.2,268.2
XS Rating Curve= 0 ,0
Exp/Cntr=0.3,0.1

Type RM Length L Ch R = 1 ,1084.5  ,291.2,288.5,281.8
XS GIS Cut Line= 3
     1838367.446       269250.01     1838348.107      269672.711
     1838356.657      269787.684
#Sta/Elev= 30
       0 1950.58      10 1946.33    34.8 1933.47    44.8 1927.03    64.7 1915.92
    79.6 1904.75   114.5 1875.02   119.5 1873.04   149.3 1871.85   154.3 1870.57
   184.2 1848.05   199.1  1839.5   204.1 1837.95   214.1 1835.96   253.9 1830.44
   255.2 1830.46   270.2 1830.97   278.8 1831.31   303.7  1834.8   308.6 1834.91
   323.6 1832.61   328.6 1832.32   383.3 1833.53   393.3 1834.73   403.2 1837.01
   418.2 1842.58     428  1847.7   447.2 1858.83   471.2 1871.17   538.4 1902.55
#Mann= 3 , 0 , 0
       0      .1       0   255.2    .045       0   270.2      .1       0
#XS Ineff= 2 , 0
                          308.24         1834.78
Permanent Ineff=
       F       F
Bank Sta=255.2,270.2
XS Rating Curve= 0 ,0
Exp/Cntr=0.3,0.1

Type RM Length L Ch R = 1 ,795.9   ,180.2,170,159.8
XS GIS Cut Line= 3
     1838231.257      269257.487     1838132.722      269417.396
     1838118.124      269766.476
#Sta/Elev= 30
       0 1957.52    49.4 1930.28      89 1912.81   123.6 1896.49   138.4 1887.83
   158.2  1873.6   163.1 1871.86   177.9 1870.49   187.8  1868.3   202.8 1861.77
   227.8 1847.23   242.7 1840.83   257.7 1832.62   262.7 1830.68   272.7 1828.47
   282.7 1827.17   287.6    1827   291.8  1827.1   306.8 1827.63   332.6 1828.39
   347.6 1827.24   357.5 1827.28   377.5 1828.76   392.5 1830.44   402.4 1833.06
   447.4 1852.49   467.3 1861.76   487.3 1872.74   517.2 1892.01   537.2 1901.57
#Mann= 3 , 0 , 0
       0      .1       0   291.8    .045       0   306.8      .1       0
Bank Sta=291.8,306.8
XS Rating Curve= 0 ,0
Exp/Cntr=0.3,0.1

Type RM Length L Ch R = 1 ,625.9   ,74.4,64,53.7
XS GIS Cut Line= 3
     1837803.672       269277.03     1837885.878      269381.096
     1838051.525       269767.24
#Sta/Elev= 30
       0 1905.67    34.4 1891.41      54 1884.79    83.5  1873.4    93.3 1869.99
   122.8 1860.95   127.7 1860.24   147.4 1859.46   157.3 1857.92   162.3  1856.7
     187 1849.05   201.8 1846.61   221.6 1839.22   246.3 1828.88   251.3 1827.57
   261.1 1825.98     271 1825.26   305.6 1824.96   315.6 1825.42   330.6 1827.09
   335.3 1827.27   340.2  1828.1   379.8 1838.12   409.4 1846.69   434.2 1854.97
   458.9 1864.68   498.4 1881.94   518.2 1890.06   542.9 1903.05   552.8 1907.72
#Mann= 3 , 0 , 0
       0      .1       0   315.6    .045       0   330.6      .1       0
Bank Sta=315.6,330.6
XS Rating Curve= 0 ,0
Exp/Cntr=0.3,0.1

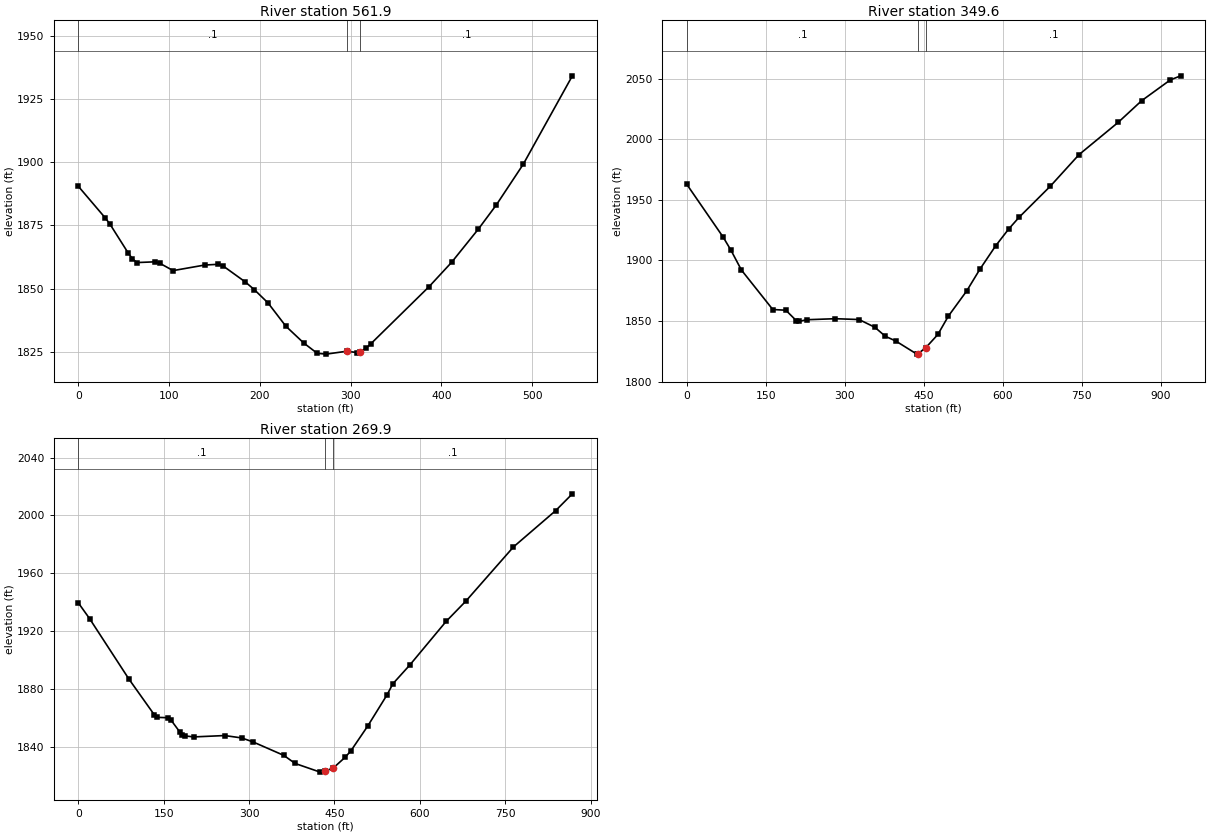
Type RM Length L Ch R = 1 ,561.9   ,197.8,212.3,226.9
XS GIS Cut Line= 4
     1837753.985      269324.225     1837832.637      269517.828
     1837936.699       269608.58      1837980.26      269800.974
#Sta/Elev= 30
       0  1890.5    29.8 1877.94    34.8 1875.58    54.7 1864.27    59.7 1861.77
    64.7 1860.31    84.6  1860.6    89.6 1860.08   104.5 1857.13   139.3 1859.33
   154.2 1859.62   159.2 1859.06   184.1 1852.62     194 1849.58     209 1844.37
   228.7 1835.14   248.4  1828.5   263.2 1824.43   273.1  1824.1   295.7 1825.24
   307.6 1824.71   310.7 1825.04   317.5 1826.56   322.4 1828.22   386.5  1850.8
   411.2 1860.37   440.8 1873.57   460.5 1883.08   490.1 1899.12   544.3 1934.15
#Mann= 3 , 0 , 0
       0      .1       0   295.7    .045       0   310.7      .1       0
Bank Sta=295.7,310.7
XS Rating Curve= 0 ,0
Exp/Cntr=0.3,0.1

Type RM Length L Ch R = 1 ,349.6   ,82.1,79.7,77.3
XS GIS Cut Line= 4
     1837655.974      269217.743     1837674.124      269499.678
     1837753.985      269782.824      1838018.98      270028.458
#Sta/Elev= 30
       0 1963.07    69.4 1919.28    84.3 1908.38   104.1 1892.08   163.6 1859.52
   188.4 1858.93   208.2 1850.36   213.1 1849.66     228 1851.08   282.5 1851.93
   327.4 1851.24   357.3 1844.87   377.3 1837.41   397.2 1833.49   437.1 1822.69
   439.4 1823.03   454.4 1828.15     477 1838.92   496.9 1854.04   531.8 1874.89
   556.8 1892.78   586.6 1912.02   611.4 1925.94   631.2 1935.64   690.6 1961.36
     745 1987.38   819.2 2013.95   863.8 2031.86   918.2 2049.01     938 2052.41
#Mann= 3 , 0 , 0
       0      .1       0   439.4    .045       0   454.4      .1       0
Bank Sta=439.4,454.4
XS Rating Curve= 0 ,0
Exp/Cntr=0.3,0.1

Type RM Length L Ch R = 1 ,269.9   ,273.6,269.9,266.1
XS GIS Cut Line= 4
      1837593.75      269246.736      1837616.74      269612.163
     1837682.649      269776.011     1837881.735      270033.251
#Sta/Elev= 30
       0 1939.51    19.8  1928.6    89.1 1886.64   133.6 1861.98   138.5  1860.2
   158.3 1859.92   163.3 1858.13   178.1 1850.23   183.1 1848.13     188 1847.34
   202.9 1846.65   257.3  1847.6     287 1845.95   306.8 1843.23   361.2 1833.85
   380.9 1828.29     425 1822.28   432.9 1822.94   447.9  1825.1   469.2 1832.68
     479 1837.05   508.4  1854.1   542.8 1875.99   552.6  1883.4   582.2  1896.3
   646.3 1926.64   680.8  1940.6   764.5 1978.14   838.5 2003.22     868 2014.91
#Mann= 3 , 0 , 0
       0      .1       0   432.9    .045       0   447.9      .1       0
Bank Sta=432.9,447.9
XS Rating Curve= 0 ,0
Exp/Cntr=0.3,0.1

Chan Stop Cuts=-1
Use User Specified Reach Order=0